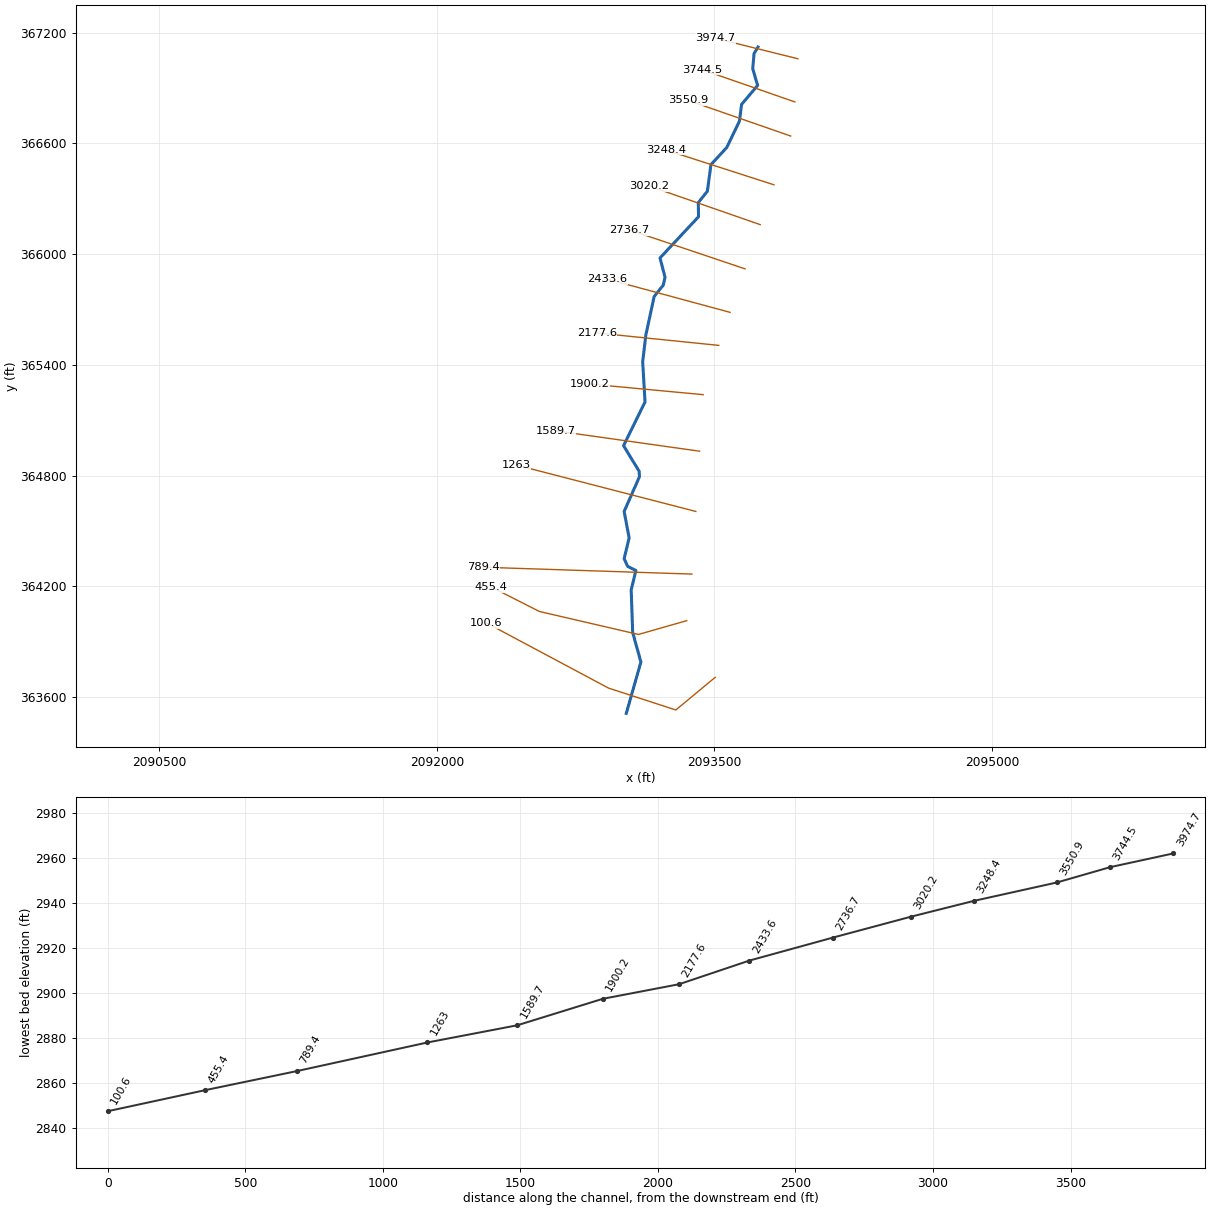
--- KuhnBranch.prj (project) ---

Proj Title=KuhnBranch
Current Plan=p01
Default Exp/Contr=0,0
English Units
Geom File=g01
Flow File=f01
Plan File=p01
BEGIN DESCRIPTION:
END DESCRIPTION:
DSS Export Rating Curves= 0
DSS Export Rating Curve Sorted= 0
DSS Export Volume Flow Curves= 0
DXF Filename=c:\KuhnBranch.
DXF OffsetX= 0
DXF OffsetY= 0
DXF ScaleX= 0
DXF ScaleY= 0

--- KuhnBranch.p01 (plan) ---

Plan Title=Floodplain
Program Version=4.00
Geom File=g01
Flow File=f01
K Sum by GR=0
Std Step Tol=0.01
Critical Tol=0.01
Num of Std Step Trials=20
Max Error Tol=0.3
Flow Tol Ratio=0.001
Split Flow NTrial=30
Split Flow Tol=0.02
Split Flow Ratio=0.02
Log Output Level=0
Friction Slope Method=1
Unsteady Friction Slope Method=2
Unsteady Bridges Friction Slope Method=1
Global Log Level=0
CheckData=False
Run HTab=0
Run UNet=0
Run PostProcess=0
UNET Theta=0
UNET Theta Warmup=0
UNET ZTol=0
UNET ZSATol=0
UNET MxIter=0
UNET MaxInSteps=0
UNET DtIC=0
UNET DtMin=0
UNET MaxCRTS=0
UNET WFStab=0
UNET SFStab=0
UNET WFX=0
UNET SFX=0
UNET DSS MLevel=0
UNET DZMax Abort=0
UNET Convert EG Bridges=0
UNET Use Existing IB Tables=0
UNET Froude Limit=0
UNET Froude Power=0
Write IC File=0
Echo Input=False
Echo Output=False
Write Detailed=0

--- KuhnBranch.f01 (steady flow) ---

Flow Title=NFF Regression Equation
Program Version=4.00
Number of Profiles=1
Profile Names=P100yr
River Rch & RM=KuhnBranch,Main      ,3974.7
588.3161
River Rch & RM=KuhnBranch,Main      ,100.6
643.7556
Boundary for River Rch & Prof#=KuhnBranch,Main      ,1
Up Type=0
Dn Type=3
Dn Slope=0.025355

--- KuhnBranch.g01 (geometry) ---

Geom Title=USGS 10m DEM
Program Version=4.10

River Reach=KuhnBranch      ,Main
Reach XY= 30
     2093735.842      367121.586     2093714.612       367085.83
     2093707.309      367004.271      2093733.94      366913.429
     2093647.527       366811.64     2093635.349      366719.754
     2093567.296      366577.787     2093481.516      366484.357
     2093462.339      366340.705      2093413.06      366278.856
     2093414.651      366202.533     2093206.293      365979.151
     2093233.384      365874.982     2093223.844       365832.05
     2093174.552      365770.038     2093130.031      365563.331
      2093112.54      365417.045      2093125.26      365199.208
     2093009.186      364962.289     2093093.459      364823.954
     2093095.049      364793.744     2093012.366      364606.117
     2093039.397      364463.012     2093012.366      364350.118
     2093031.447      364308.776     2093075.969      364286.516
     2093050.528      364181.572     2093058.478      363951.014
     2093102.999      363790.418     2093023.824      363512.487

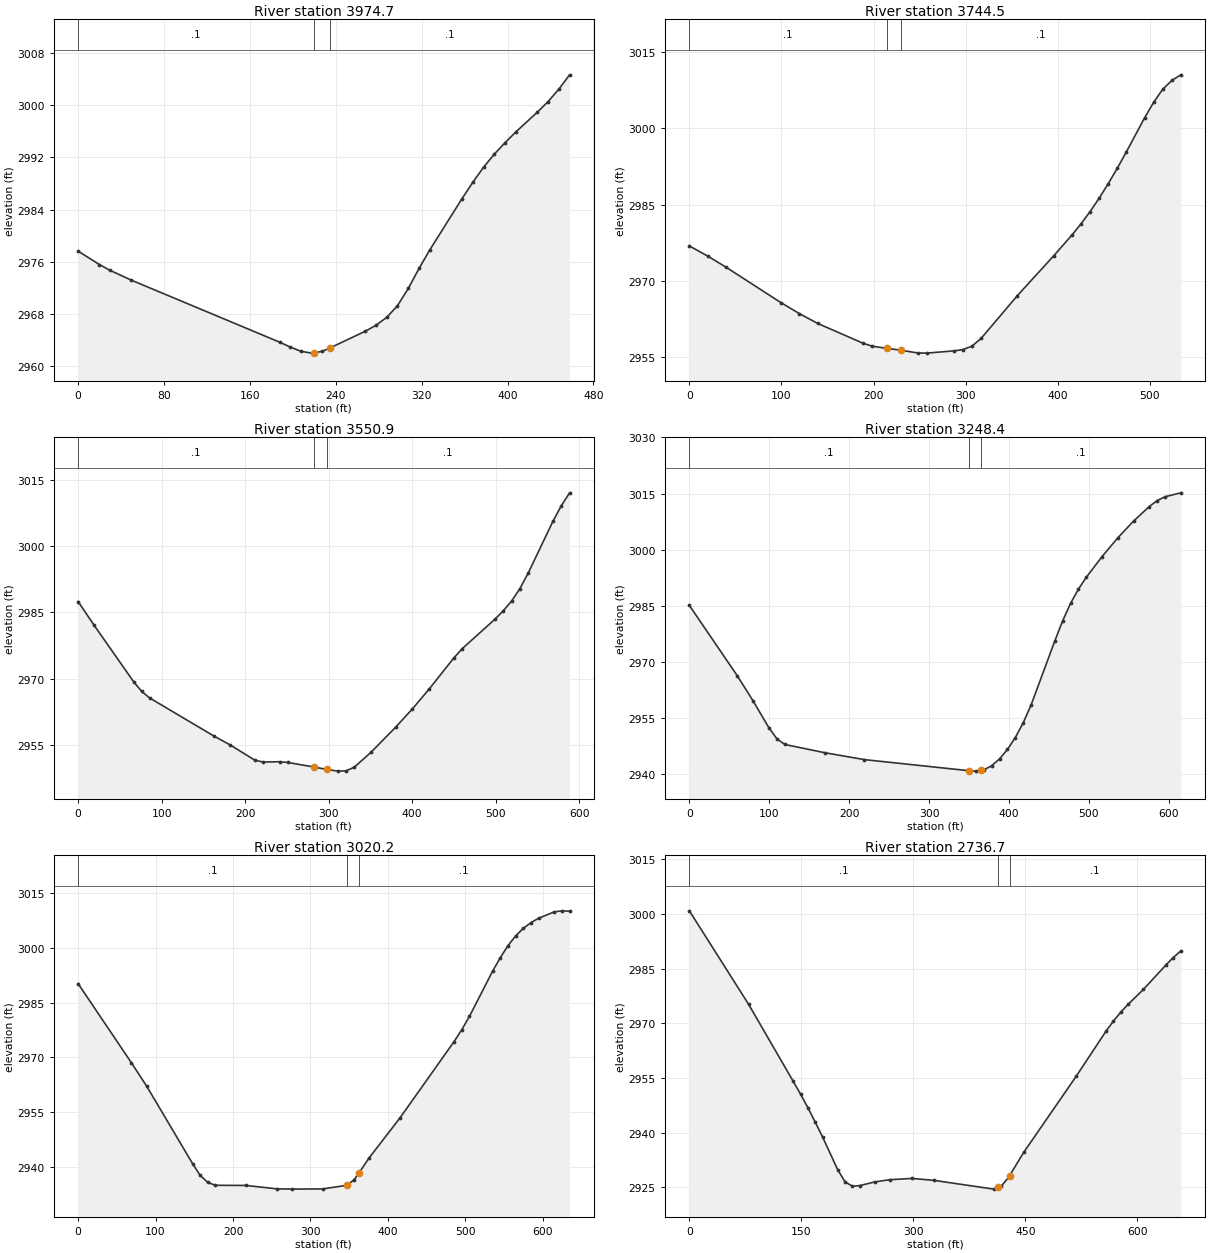
Type RM Length L Ch R = 1 ,3974.7  ,232.5,230.2,228.2
XS GIS Cut Line= 3
     2093951.422      367058.091     2093730.737      367112.987
     2093507.141      367168.608
#Sta/Elev= 28
       0 2977.61    19.8 2975.55    29.7 2974.66    49.4 2973.16   187.9 2963.61
   197.8 2962.86   207.6 2962.22   217.5 2961.94   219.9 2962.01   227.4 2962.21
   234.9 2962.76   267.5  2965.3   277.5 2966.22   287.5 2967.44   297.5 2969.23
   307.6 2971.89   317.6 2974.96   327.6  2977.8   357.6 2985.67   367.7 2988.19
   377.7  2990.5   387.7 2992.51   397.7 2994.27   407.7 2995.91   427.8 2998.96
   437.8 3000.58   447.8 3002.49   457.8 3004.69
#Mann= 3 , 0 , 0
       0      .1       0   219.9    .045       0   234.9      .1       0
Bank Sta=219.9,234.9
XS Rating Curve= 0 ,0
Exp/Cntr=0.3,0.1

Type RM Length L Ch R = 1 ,3744.5  ,193.1,193.6,193.9
XS GIS Cut Line= 3
     2093935.468      366824.108     2093804.021      366869.911
     2093431.546        366999.7
#Sta/Elev= 30
       0 2976.88    19.9 2974.89    39.8 2972.71    99.4 2965.75   119.3 2963.61
   139.2 2961.67   188.5 2957.78   198.4  2957.2   214.5 2956.76   229.5 2956.41
   247.7 2955.87   257.5 2955.83   287.1 2956.27     297 2956.52   306.8  2957.2
   316.7 2958.71   356.1 2967.12   395.6 2974.95   415.3 2979.01   425.2 2981.22
     435 2983.61   444.9 2986.25   454.8 2989.12   464.6 2992.14   474.5 2995.37
   494.2 3002.03   504.1 3005.09   513.9 3007.65   523.8 3009.38   533.6 3010.49
#Mann= 3 , 0 , 0
       0      .1       0   214.5    .045       0   229.5      .1       0
Bank Sta=214.5,229.5
XS Rating Curve= 0 ,0
Exp/Cntr=0.3,0.1

Type RM Length L Ch R = 1 ,3550.9  ,302,302.5,302.9
XS GIS Cut Line= 3
      2093912.67      366639.378     2093768.853      366689.491
     2093356.948      366833.021
#Sta/Elev= 30
       0 2987.46      19 2982.13    66.6 2969.25    76.2 2967.08    85.7  2965.6
   162.2 2957.02     182 2954.97   211.8 2951.48   221.7 2951.08   241.5 2951.15
   251.4 2950.98   282.6 2949.94   297.6 2949.41   310.9 2949.02   320.8 2949.08
   330.7 2949.91   350.6 2953.27   380.3 2958.99   400.1 2963.09     420 2967.54
   449.7 2974.63   459.6 2976.72   499.3 2983.49   509.2 2985.39   519.1 2987.58
     529 2990.39   538.9  2993.9   568.7  3005.7   578.6 3009.18   588.5  3012.1
#Mann= 3 , 0 , 0
       0      .1       0   282.6    .045       0   297.6      .1       0
Bank Sta=282.6,297.6
XS Rating Curve= 0 ,0
Exp/Cntr=0.3,0.1

Type RM Length L Ch R = 1 ,3248.4  ,228.2,228.2,228.1
XS GIS Cut Line= 3
     2093822.129      366375.302     2093471.394      366488.544
     2093236.692      366564.323
#Sta/Elev= 30
       0  2985.1    59.8 2966.36    79.7 2959.61    99.6 2952.39   109.6 2949.45
   119.5 2947.94   169.3 2945.75   219.2 2943.89     350 2940.93   358.6 2940.82
     365 2941.04   368.6 2941.17   378.4 2942.26   388.3 2944.11   398.2 2946.63
     408  2949.8   417.9 2953.73   427.8 2958.52   457.4 2975.57   467.2 2980.95
   477.1 2985.61     487 2989.44   496.8  2992.6   516.5 2998.12   536.3 3003.16
     556 3007.62   575.7 3011.52   585.6 3013.12   595.5 3014.14   615.2 3015.18
#Mann= 3 , 0 , 0
       0      .1       0     350    .045       0     365      .1       0
Bank Sta=350,365
XS Rating Curve= 0 ,0
Exp/Cntr=0.3,0.1

Type RM Length L Ch R = 1 ,3020.2  ,283.3,283.5,283.7
XS GIS Cut Line= 3
     2093748.132      366159.476     2093543.608      366230.743
     2093148.945      366368.264
#Sta/Elev= 30
       0 2990.21    68.9 2968.47    88.6 2962.04   147.7 2940.83   157.5 2937.61
   167.4 2935.66   177.2 2934.86   216.6 2934.82   256.4 2933.89   276.3 2933.81
   316.1 2933.88     346 2934.83   347.3 2935.03   355.9 2936.28   362.3 2938.17
   375.8 2942.41   415.6 2953.38   485.3 2974.29   495.2 2977.52   505.2 2981.22
     535  2993.6     545 2997.32   554.9 3000.62   564.9 3003.33   574.8  3005.4
   584.8 3006.98   594.7 3008.18   614.6  3009.9   624.6  3010.2   634.5 3010.09
#Mann= 3 , 0 , 0
       0      .1       0   347.3    .045       0   362.3      .1       0
Bank Sta=347.3,362.3
XS Rating Curve= 0 ,0
Exp/Cntr=0.3,0.1

Type RM Length L Ch R = 1 ,2736.7  ,301.9,303.1,304.3
XS GIS Cut Line= 3
     2093666.028      365920.008     2093336.746       366031.17
     2093042.531      366130.494
#Sta/Elev= 30
       0 3000.84    79.4 2975.18     139 2954.11     149 2950.54   158.9 2946.78
   168.8  2942.8   178.7 2938.69   198.6 2929.86   208.5 2926.51   218.4 2925.32
   228.4 2925.51   248.2  2926.5   268.1 2927.11   297.9 2927.46   327.7 2926.93
   407.6 2924.53   413.8 2925.03   417.7 2925.35   427.7 2927.83   428.8 2928.22
   447.7 2934.61   517.8 2955.42   557.9 2967.83   567.9 2970.63   577.9 2973.11
     588  2975.3     608 2979.29     638 2985.97     648 2988.04   658.1 2989.85
#Mann= 3 , 0 , 0
       0      .1       0   413.8    .045       0   428.8      .1       0
#XS Ineff= 2 , 0
          298.23 2927.37
Permanent Ineff=
       F       F
Bank Sta=413.8,428.8
XS Rating Curve= 0 ,0
Exp/Cntr=0.3,0.1

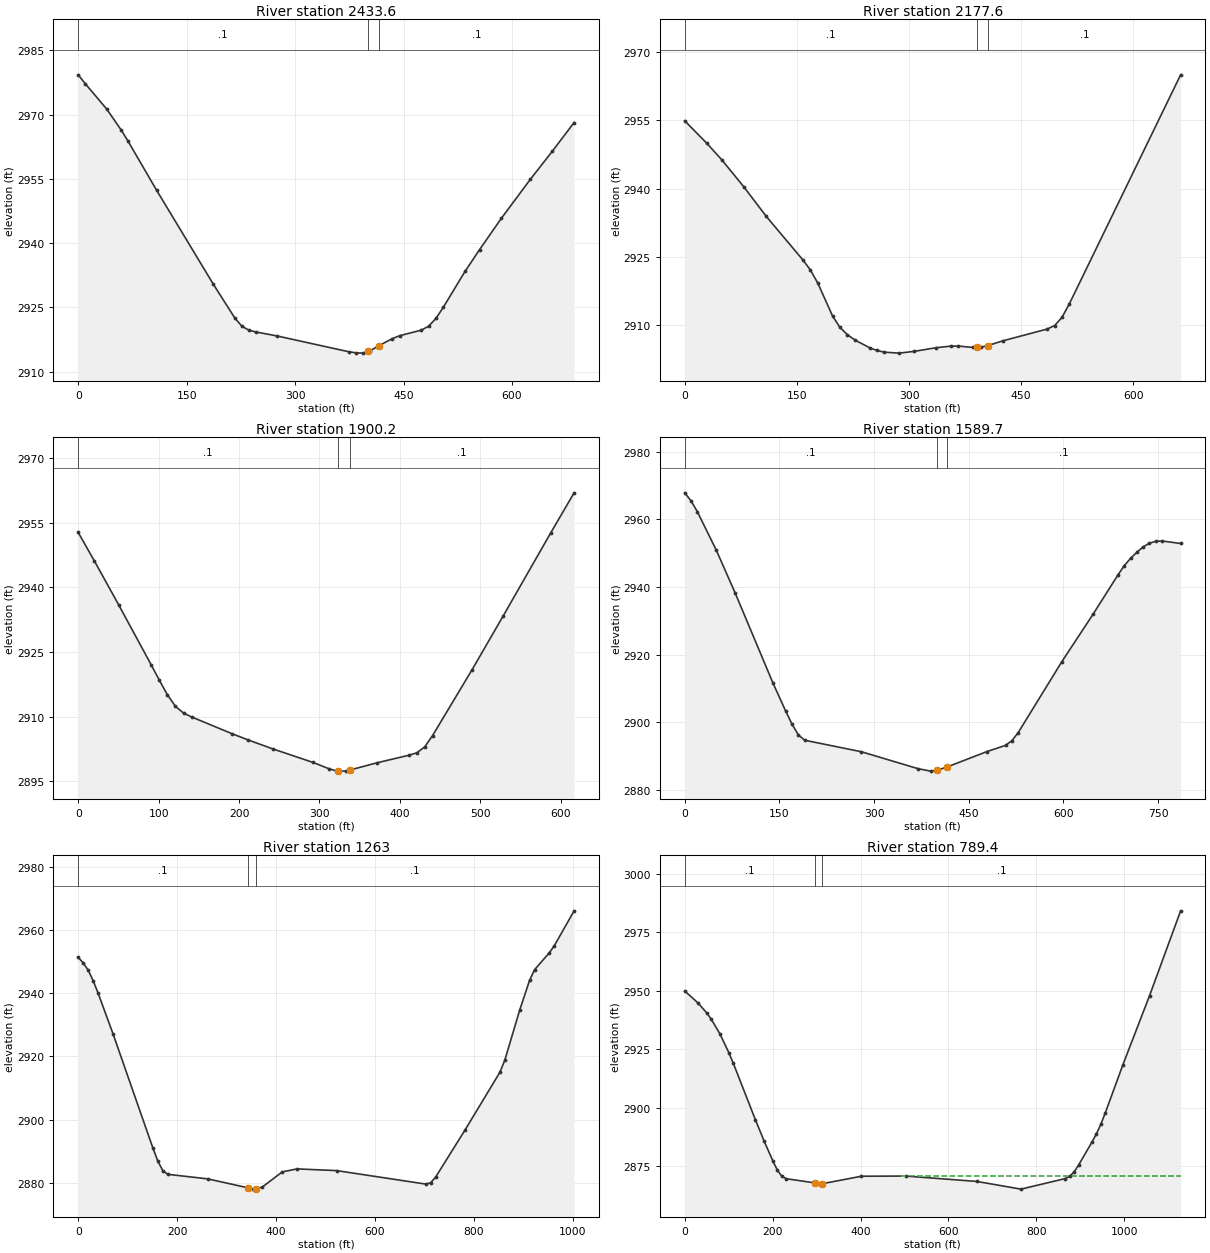
Type RM Length L Ch R = 1 ,2433.6  ,252.6,256,259.3
XS GIS Cut Line= 3
     2093585.262      365684.438     2093224.259      365782.314
     2092923.229       365863.93
#Sta/Elev= 30
       0 2979.27     9.8 2977.19    39.4 2971.29    59.1 2966.48    68.9  2963.8
   108.3 2952.38     187 2930.39   216.6 2922.54   226.4 2920.62   236.2 2919.67
   246.1 2919.27   275.6 2918.33     374 2914.67   384.1 2914.41   394.2 2914.34
   400.6 2914.72   404.2 2914.93   415.6 2916.04   434.4 2917.72   444.5  2918.4
   474.6  2919.7   484.7 2920.63   494.8 2922.43   504.8 2924.99     535 2933.39
   555.1 2938.48   585.3 2945.79   625.6 2954.94   655.8 2961.44   685.9 2968.14
#Mann= 3 , 0 , 0
       0      .1       0   400.6    .045       0   415.6      .1       0
Bank Sta=400.6,415.6
XS Rating Curve= 0 ,0
Exp/Cntr=0.3,0.1

Type RM Length L Ch R = 1 ,2177.6  ,277.2,277.4,277.6
XS GIS Cut Line= 3
     2093523.934      365505.567     2093169.859      365541.728
     2092864.159      365572.948
#Sta/Elev= 30
       0 2954.92    29.7 2949.95    49.4 2946.37    79.1 2940.39   108.8 2933.95
   158.2 2924.28   168.1 2922.11     178 2919.21   197.7 2911.98   207.6 2909.47
   217.5 2907.89   227.4 2906.73   247.2    2905     257 2904.41   266.9 2904.03
   286.7 2903.82   306.5  2904.2   336.1 2905.01   355.9 2905.36   365.8 2905.38
   385.6 2905.06   390.5 2905.09   395.6 2905.12   405.5 2905.48   425.3 2906.52
   484.8 2909.12   494.7 2909.89   504.6  2911.7   514.5  2914.7   663.2 2965.04
#Mann= 3 , 0 , 0
       0      .1       0   390.5    .045       0   405.5      .1       0
Bank Sta=390.5,405.5
XS Rating Curve= 0 ,0
Exp/Cntr=0.3,0.1

Type RM Length L Ch R = 1 ,1900.2  ,312,310.5,309.1
XS GIS Cut Line= 3
     2093439.539      365238.703     2093088.521      365271.649
     2092825.613      365296.326
#Sta/Elev= 27
       0  2952.7    20.2 2946.07    50.4 2935.88    90.7 2922.01   100.7 2918.49
   110.8 2915.07   120.9 2912.36     131  2910.8     141  2909.9   191.4    2906
   211.5 2904.55   241.8  2902.5   292.1 2899.34   312.3 2897.85   322.3 2897.33
   322.5 2897.33   332.4 2897.35   337.5 2897.57   372.1 2899.29   411.2 2901.02
     421 2901.57   430.8 2902.94   440.6 2905.57   489.5 2920.78   528.6 2933.39
   587.3 2952.53   616.6  2961.9
#Mann= 3 , 0 , 0
       0      .1       0   322.5    .045       0   337.5      .1       0
Bank Sta=322.5,337.5
XS Rating Curve= 0 ,0
Exp/Cntr=0.3,0.1

Type RM Length L Ch R = 1 ,1589.7  ,328.4,326.7,325
XS GIS Cut Line= 3
     2093420.264      364932.451     2093063.867      364982.883
      2092642.16      365042.558
#Sta/Elev= 30
       0 2967.85      10 2965.48      20 2962.27      50  2950.9      80 2938.21
     140 2911.54     160 2903.33     170 2899.47     180 2896.31     190 2894.72
     280 2891.31   369.8  2886.3   389.7 2885.58   400.4 2885.86   415.4 2886.78
   478.8 2891.35   508.5  2893.2   518.4 2894.57   528.3 2896.91   597.7 2917.95
   647.2 2931.98   686.8 2943.64   696.7 2946.34   706.6 2948.49   716.5 2950.28
   726.4 2951.85   736.3 2952.94   746.2 2953.49   756.1 2953.62   785.9 2952.88
#Mann= 3 , 0 , 0
       0      .1       0   400.4    .045       0   415.4      .1       0
Bank Sta=400.4,415.4
XS Rating Curve= 0 ,0
Exp/Cntr=0.3,0.1

Type RM Length L Ch R = 1 ,1263    ,465.8,473.6,479.1
XS GIS Cut Line= 3
      2093399.73      364606.179     2093077.703      364689.574
     2092428.647       364857.66
#Sta/Elev= 30
       0 2951.39    10.1 2949.67    20.2 2947.34    30.2 2944.03    40.3 2940.05
    70.6 2927.08   151.2 2890.92   161.3 2886.71   171.4 2883.74   181.4 2882.63
   262.1 2881.19     344 2878.33   352.7 2877.94     359 2877.94   372.7 2878.63
   412.7  2883.4   442.7 2884.35   522.8 2883.81   702.9 2879.54   712.9 2879.95
   722.9 2881.73     783 2896.81     853 2914.98     863 2918.84     893 2934.65
     913 2944.09   923.1 2947.49   953.1 2952.88   963.1  2955.1  1003.1 2966.16
#Mann= 3 , 0 , 0
       0      .1       0     344    .045       0     359      .1       0
Bank Sta=344,359
XS Rating Curve= 0 ,0
Exp/Cntr=0.3,0.1

Type RM Length L Ch R = 1 ,789.4   ,339.8,334,329
XS GIS Cut Line= 3
     2093378.378      364266.926     2093026.944      364278.486
     2092250.628      364304.024
#Sta/Elev= 30
       0 2949.92    30.1 2944.83    50.2 2940.51    60.3 2937.89    80.4 2931.48
   100.5  2923.5   110.5 2919.04   160.7 2894.94   180.8 2885.72   200.9 2877.13
     211 2873.27     221 2870.72   231.1  2869.7   297.3 2867.88   312.3 2867.54
   402.1 2870.76   502.9 2870.84   664.3 2868.54   765.2 2865.25   866.1 2869.77
   876.2 2870.71   886.3 2872.69   896.4  2875.6   926.6 2885.33   936.7 2888.81
   946.8 2892.93   956.9  2897.8   997.2 2918.47  1057.8 2947.97  1128.4 2984.18
#Mann= 3 , 0 , 0
       0      .1       0   297.3    .045       0   312.3      .1       0
#XS Ineff= 2 , 0
                          491.05         2870.87
Permanent Ineff=
       F       F
Bank Sta=297.3,312.3
XS Rating Curve= 0 ,0
Exp/Cntr=0.3,0.1

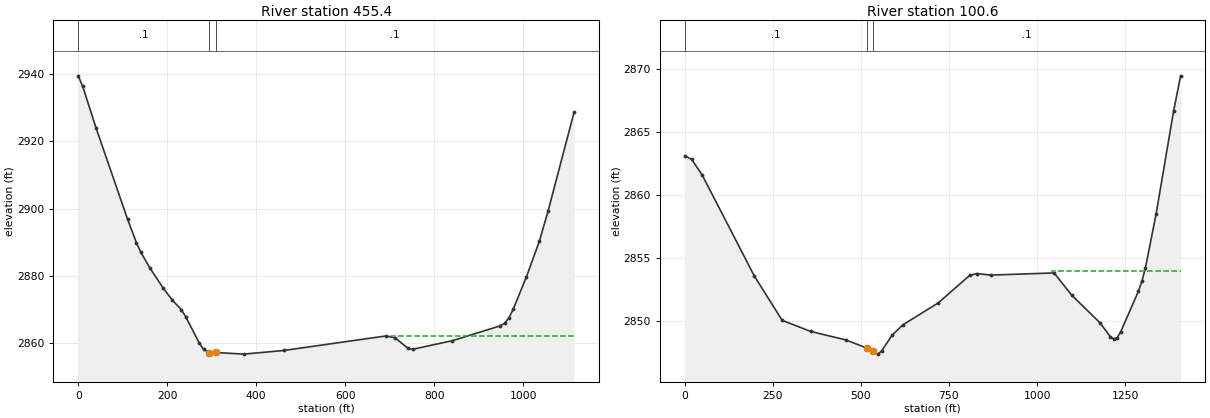
Type RM Length L Ch R = 1 ,455.4   ,355.7,354.8,353.1
XS GIS Cut Line= 4
     2093350.933       364014.66     2093089.553       363939.98
     2092554.348      364064.446     2092292.969      364197.211
#Sta/Elev= 30
       0 2939.51    10.1 2936.37    40.3 2923.92   110.8 2896.93   130.9 2889.87
     141 2886.99   161.1 2882.37   191.3 2876.33   211.4 2872.84   231.6    2870
   241.6 2867.87   271.8 2860.11   281.8 2858.19   294.8 2857.14   309.8 2857.25
   371.8 2856.76   461.7 2857.84   691.4 2862.16   711.4 2861.64   741.4  2858.5
   751.4  2858.2   840.9 2860.76   948.4 2865.17   958.1 2865.94   967.9 2867.53
   977.7 2870.16    1007 2879.65  1036.3 2890.32  1055.9 2899.29  1114.5 2928.75
#Mann= 3 , 0 , 0
       0      .1       0   294.8    .045       0   309.8      .1       0
#XS Ineff= 2 , 0
                          702.57         2862.11
Permanent Ineff=
       F       F
Bank Sta=294.8,309.8
XS Rating Curve= 0 ,0
Exp/Cntr=0.3,0.1

Type RM Length L Ch R = 1 ,100.6   ,99.9,100.6,101.3
XS GIS Cut Line= 4
     2093504.441      363707.643     2093291.689      363530.934
     2092927.747      363649.559     2092268.076      364002.213
#Sta/Elev= 30
       0  2863.1    19.8 2862.81    49.4 2861.59   197.6 2853.58   276.6 2850.07
   357.2 2849.19   457.9 2848.51   518.5 2847.85   533.5  2847.6   548.6 2847.39
   558.6 2847.64   588.8 2848.89   619.1 2849.71   719.2 2851.44     809 2853.63
   828.9 2853.77   868.8 2853.65  1048.3 2853.82  1098.2 2852.06    1178 2849.89
  1207.9 2848.78  1217.9 2848.58  1227.8  2848.7  1237.8 2849.18  1287.7 2852.38
  1297.7 2853.18  1307.6 2854.23  1337.6 2858.45  1387.4 2866.63  1407.4 2869.43
#Mann= 3 , 0 , 0
       0      .1       0   518.5    .045       0   533.5      .1       0
#XS Ineff= 2 , 0
                         1041.63         2853.95
Permanent Ineff=
       F       F
Bank Sta=518.5,533.5
XS Rating Curve= 0 ,0
Exp/Cntr=0.3,0.1

Chan Stop Cuts=-1
Use User Specified Reach Order=0
Composite Channel Slope=5